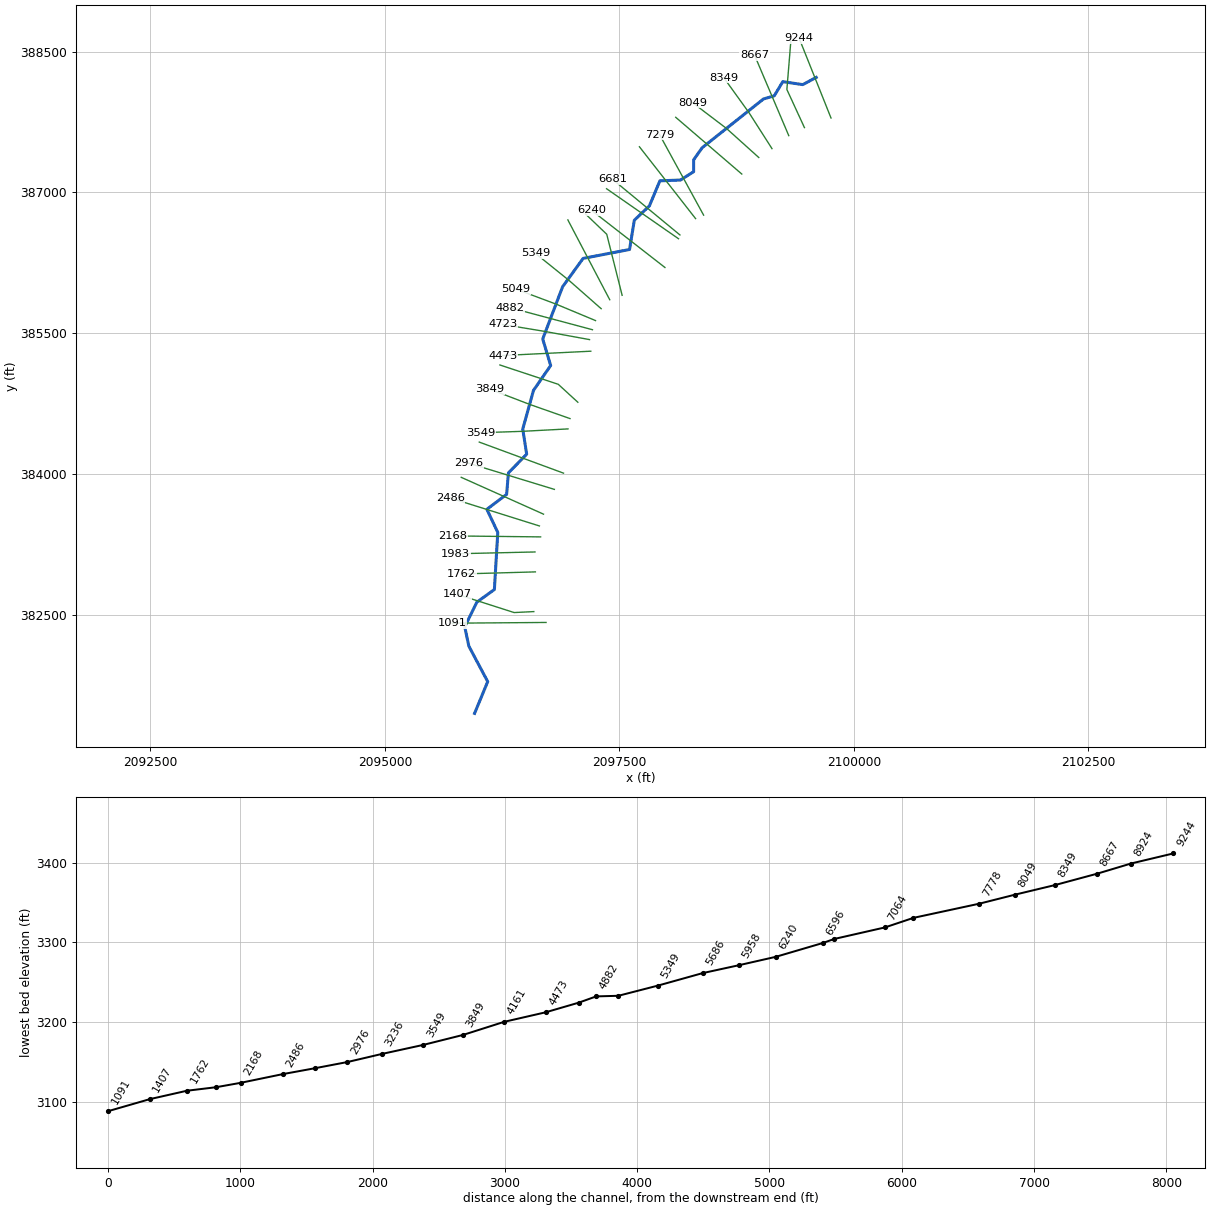
--- JOBKNOBBR1.prj (project) ---

Proj Title=JOBKNOBBR1
Current Plan=p01
Default Exp/Contr=0,0
English Units
Geom File=g01
Flow File=f01
Plan File=p01
BEGIN DESCRIPTION:
Stream Name- Job Knobb River 1
Flood Zone: Zone A
Greenbrier County, WV
County-Wide Study
WVDHSEM-2018-3, Flood Risk Project
HEC-RAS Version: 5.0.7
General Notes:
For the Hydrology regression was used.
END DESCRIPTION:
DSS Export Rating Curves= 0
DSS Export Rating Curve Sorted= 0
DSS Export Volume Flow Curves= 0
DXF OffsetX= 0
DXF OffsetY= 0
DXF ScaleX= 0
DXF ScaleY= 0

--- JOBKNOBBR1.p01 (plan) ---

Plan Title=Floodplain
Program Version=5.07
Short Identifier=Floodplain
Geom File=g01
Flow File=f01
Subcritical Flow
K Sum by GR= 0
Std Step Tol= 0.01
Critical Tol= 0.01
Num of Std Step Trials= 20
Max Error Tol= 0.3
Flow Tol Ratio= 0.001
Split Flow NTrial= 30
Split Flow Tol= 0.02
Split Flow Ratio= 0.02
Log Output Level= 0
Friction Slope Method= 1
Unsteady Friction Slope Method= 2
Unsteady Bridges Friction Slope Method= 1
Parabolic Critical Depth
Global Vel Dist= 0 , 0 , 0
Global Log Level= 0
CheckData=True
Encroach Param=-1 ,0,0, 0
Mapping Interval=1HOUR
Computation Time Step Use Courant=        0
Computation Time Step Use Time Series=    0
Computation Time Step Count To Double=0
Computation Time Step Max Doubling=0
Computation Time Step Max Halving=0
Computation Time Step Residence Courant=0
Run HTab= 0
Run UNet= 0
Run Sediment= 0
Run PostProcess= 0
Run WQNet= 0
Run RASMapper= 0
UNET Theta= 0
UNET Theta Warmup= 0
UNET ZTol= 0
UNET ZSATol= 0
UNET MxIter= 0
UNET Max Iter WO Improvement= 0
UNET MaxInSteps= 0
UNET DtIC= 0
UNET DtMin= 0
UNET MaxCRTS= 0
UNET WFStab= 0
UNET SFStab= 0
UNET WFX= 1
UNET SFX= 1
UNET 1D Methodology=Finite Difference
UNET DSS MLevel= 1
UNET Pardiso=0
UNET DZMax Abort= 0
UNET Use Existing IB Tables= 0
UNET Froude Reduction=False
UNET Froude Limit= 0
UNET Froude Power= 0
UNET D1 Cores= 0
UNET D2 Coriolis=0
UNET D2 Cores= 0
UNET D2 Theta= 1
UNET D2 Theta Warmup= 1
UNET D2 Z Tol= 0.01
UNET D2 Volume Tol= 0.01
UNET D2 Max Iterations= 20
UNET D2 Equation= 0
UNET D2 RampUpFraction=0.1
UNET D2 TimeSlices= 1
UNET D2 BCVolumeCheck=0
UNET D1D2 MaxIter= 0
UNET D1D2 ZTol=0.01
UNET D1D2 QTol=0.1
UNET D1D2 MinQTol=1
Write IC File= 0
Write IC File at Fixed DateTime=0
Write IC File at Sim End=0
Echo Input=False
Echo Parameters=False
Echo Output=False
Write Detailed= 0
HDF Write Warmup=0
HDF Write Time Slices=0
HDF Flush=0
HDF Face Node Velocities=0
HDF Compression= 1
HDF Chunk Size= 1
HDF Spatial Parts= 1
HDF Use Max Rows=0
HDF Fixed Rows= 1
Calibration Method= 0
Calibration Iterations= 20
Calibration Max Change=0.05
Calibration Tolerance=0.2
Calibration Maximum=1.5
Calibration Minimum=0.5
Calibration Optimization Method= 1
WQ AD Non Conservative
WQ ULTIMATE=-1
WQ Max Comp Step=1HOUR
WQ Output Interval=15MIN
WQ Output Selected Increments= 0
WQ Output face flow=0
WQ Output face velocity=0
WQ Output face area=0
WQ Output face dispersion=0
WQ Output cell volume=0
WQ Output cell surface area=0
WQ Output cell continuity=0
WQ Output cumulative cell continuity=0
WQ Output face conc=0
WQ Output face dconc_dx=0
WQ Output face courant=0
WQ Output face peclet=0
WQ Output face adv mass=0
WQ Output face disp mass=0
WQ Output cell mass=0
WQ Output cell source sink temp=0
WQ Output nsm pathways=0
WQ Output nsm derived pathways=0
WQ Output MaxMinRange=-1
WQ Daily Max Min Mean=-1
WQ Daily Range=0
WQ Daily Time=0
WQ Create Restart=0
WQ Fixed Restart=0
WQ System Summary=0
WQ Write To DSS=0
WQ Use Fixed Temperature=0
Sorting and Armoring Iterations= 10
XS Update Threshold= 0.02
Bed Roughness Predictor= 0
Hydraulics Update Threshold= 0.02
Energy Slope Method= 1
Volume Change Method= 1
Sediment Retention Method= 0
XS Weighting Method= 0
Number of US Weighted Cross Sections= 1
Number of DS Weighted Cross Sections= 1
Upstream XS Weight=0
Main XS Weight=1
Downstream XS Weight=0
Number of DS XS's Weighted with US Boundary= 1
Upstream Boundary Weight= 1
Weight of XSs Associated with US Boundary= 0
Number of US XS's Weighted with DS Boundary= 1
Downstream Boundary Weight= 0.5
Weight of XSs Associated with DS Boundary= 0.5
Percentile Method= 0
Sediment Output Level= 3
Mass or Volume Output= 0
Output Increment Type= 1
Profile and TS Output Increment= 1
XS Output Flag= 0
XS Output Increment= 10
Write Gradation File= 0
Read Gradation Hotstart= 0
Write HDF5 File= 1
Write Binary Output= 1
Write DSS Sediment File= 0
SV Curve= 0
Specific Gage Flag= 0

--- JOBKNOBBR1.f01 (steady flow) ---

Flow Title=H3a_CombinedFlows
Program Version=5.07
Number of Profiles= 6
Profile Names=f1p,f10p,f4p,f2p,f02p,f1pplus
River Rch & RM=JOBKNOBBR1,Main            ,9244
     562     297     395     476     786     832
River Rch & RM=JOBKNOBBR1,Main            ,5686
     630     334     443     533     878     931
River Rch & RM=JOBKNOBBR1,Main            ,5049
     960     518     682     816    1330    1420
River Rch & RM=JOBKNOBBR1,Main            ,1
    1620     892    1160    1380    2220    2400
Boundary for River Rch & Prof#=JOBKNOBBR1,Main            , 1
Up Type= 0
Dn Type= 1
Dn Known WS=3061.56
Boundary for River Rch & Prof#=JOBKNOBBR1,Main            , 2
Up Type= 0
Dn Type= 1
Dn Known WS=3060.31
Boundary for River Rch & Prof#=JOBKNOBBR1,Main            , 3
Up Type= 0
Dn Type= 1
Dn Known WS=3060.8
Boundary for River Rch & Prof#=JOBKNOBBR1,Main            , 4
Up Type= 0
Dn Type= 1
Dn Known WS=3061.18
Boundary for River Rch & Prof#=JOBKNOBBR1,Main            , 5
Up Type= 0
Dn Type= 1
Dn Known WS=3062.73
Boundary for River Rch & Prof#=JOBKNOBBR1,Main            , 6
Up Type= 0
Dn Type= 1
Dn Known WS=3063.02
DSS Import GetInterval= 0
DSS Import GetPeak= 0
DSS Import FillOption= 0

--- JOBKNOBBR1.g01 (geometry) ---

Geom Title=Geometry
Program Version=5.07

River Reach=JOBKNOBBR1      ,Main
Reach XY= 30
2099597.73500003388226.2530000062099454.20000003388149.294000015
2099241.19200002 388180.799000012099150.28200001388029.795000017
2099035.38200003387996.1949999932098381.15799998387476.024000019
2098290.90600003387347.6680000132098290.99000001387221.327000022
2098150.76300001387132.2070000172097930.86600001387123.438999996
2097819.23400001386856.6540000142097658.52200001386703.709999993
2097607.51100002386391.6770000012097112.27299999386296.429000005
2096893.51199999385993.6260000172096681.90800002385437.322999999
2096766.55600001385154.8589999972096583.55400002384889.618000001
2096468.91000001384476.7399999952096510.79600002384209.443000004
2096316.30600001384009.866999999     2096296.844383781.099000007
2096086.42900002383621.4379999942096202.75399998383375.263999999
2096166.63183324382766.6260871122095979.82329602382631.828356134
2095850.51900002382369.2090000212095894.26900001382162.959000021
2096095.45899999381784.4800000192095955.29099999381446.046000019

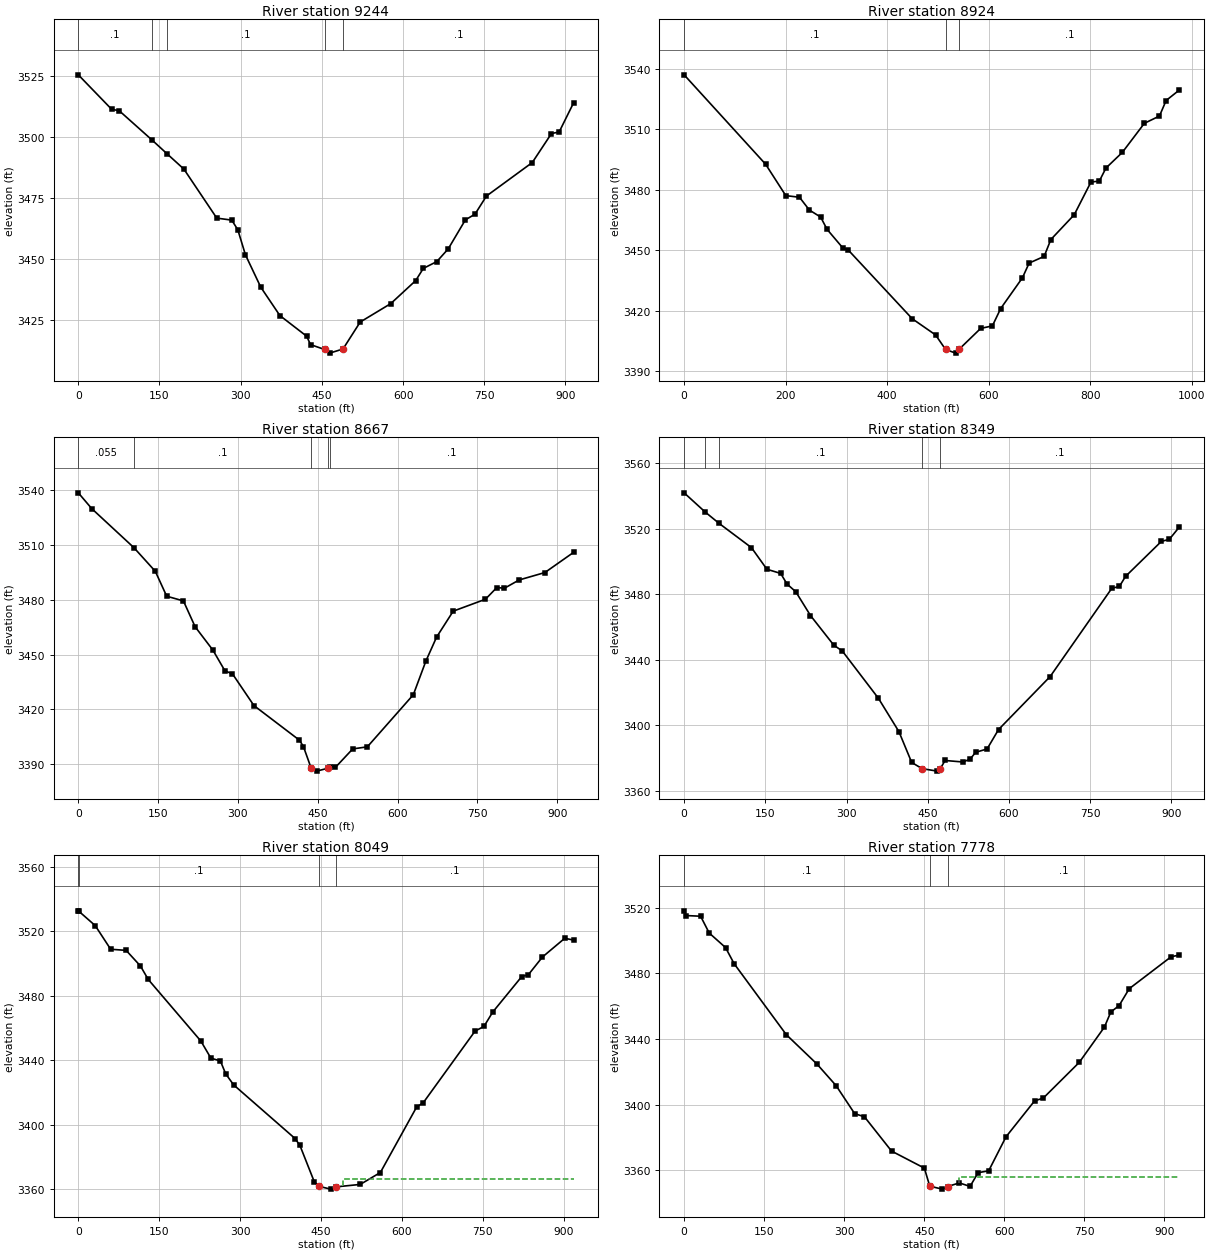
Type RM Length L Ch R = 1 ,9244    ,326,320.7,312.1
XS GIS Cut Line= 2
2099755.50318589387793.1928664952099416.01855844388642.793138319
#Sta/Elev= 30
       0 3525.56    61.5 3511.47    75.7 3510.83   135.43499.017  164.763493.053
   195.1 3486.94   255.8 3466.87   283.5 3466.05   294.7 3462.08   308.7 3451.87
   337.1 3438.58   372.4 3426.96   421.9 3418.49     429 3415.06     455 3413.07
   464.3 3411.57     489 3413.26   520.8 3424.31   577.3 3431.86   623.3 3441.28
   637.4 3446.28   662.2 3449.05   683.3 3454.24   715.1 3466.16   732.8 3468.47
     754 3475.91   838.7 3489.64   874.1 3501.51   888.3 3502.14   914.9 3514.05
#Mann= 5 ,-1 , 0
       0      .1       0   135.4     .06       0  164.76      .1       0
     455    .045       0     489      .1       0
Bank Sta=455,489
XS Rating Curve= 0 ,0
Exp/Cntr=0.3,0.1

Type RM Length L Ch R = 1 ,8924    ,242.1,256.4,253.5
XS GIS Cut Line= 3
2099472.05994922387691.3602256242099284.89905252388097.355401545
2099328.09002868388624.285310719
#Sta/Elev= 30
       0    3537   160.6 3492.63   200.3 3477.06   227.3 3476.25   246.7 3469.92
     269 3466.41   281.7 3460.31   312.3 3451.22   323.2 3450.12   449.4 3415.98
   495.5 3407.92   515.2 3400.71     535  3398.9   542.2 3400.91   584.3 3411.16
   607.4 3412.42   623.8 3421.04   666.6 3436.28   679.8 3443.58   709.4 3446.91
   722.6 3455.27   768.7 3467.58   801.6  3483.8   818.1 3484.26   831.2 3490.75
   863.5 3498.53   906.9 3512.95   936.6 3516.55   949.7 3524.25   975.8 3529.47
#Mann= 3 ,-1 , 0
       0      .1       0   515.2    .045       0   542.2      .1       0
Bank Sta=515.2,542.2
XS Rating Curve= 0 ,0
Exp/Cntr=0.3,0.1

Type RM Length L Ch R = 1 ,8667    ,315.5,318.6,320.6
XS GIS Cut Line= 2
2099304.94261378387605.6420090952098940.88465044388461.968022411
#Sta/Elev= 30
       0  3538.6    25.3 3529.94  104.563508.535   144.7 3495.59   166.1 3481.95
   197.5 3479.38   219.5 3465.22     253 3452.38   275.5 3441.07   289.7  3439.4
     330 3422.04   415.6 3403.05   423.1 3399.49   437.3 3387.91   447.7 3386.12
   469.4 3387.73   472.6 3388.59   483.1 3388.18   515.6 3398.29   543.1 3399.43
   629.5 3427.99   653.2 3446.52   673.2 3459.56   704.4 3473.76     765  3480.3
   786.4 3486.72   800.6 3486.33   828.3 3490.86   876.7 3494.93   930.5 3505.96
#Mann= 5 ,-1 , 0
       0    .055       0  104.56      .1       0   437.3    .045       0
   469.4    .045       0   472.6      .1       0
Bank Sta=437.3,469.4
XS Rating Curve= 0 ,0
Exp/Cntr=0.3,0.1

Type RM Length L Ch R = 1 ,8349    ,294.4,300,303.1
XS GIS Cut Line= 3
     2099126.308      387466.657     2098881.421      387849.648
     2098612.507      388223.031
#Sta/Elev= 30
       0 3541.83    38.63530.196   64.693523.144   124.4 3508.35   152.9 3495.15
   178.3 3492.62   190.1 3486.11   206.2 3481.45   233.4  3466.9   276.3 3448.87
   292.3 3445.18   358.8 3416.39   396.8 3395.96   420.3 3377.19   439.5  3373.4
   467.5 3371.88   472.6 3373.07     482 3378.38   514.9 3377.46   528.2 3379.18
   538.4 3383.36   559.6 3385.42   580.7 3397.25   676.1 3429.65   789.9 3483.51
     804 3484.68   815.3 3490.79   881.6 3512.21   896.1 3513.39   914.7 3520.97
#Mann= 5 ,-1 , 0
       0      .1       0    38.6     .06       0   64.69      .1       0
   439.5    .045       0   472.6      .1       0
Bank Sta=439.5,472.6
XS Rating Curve= 0 ,0
Exp/Cntr=0.3,0.1

Type RM Length L Ch R = 1 ,8049    ,269.8,270.3,269.8
XS GIS Cut Line= 3
     2098985.249      387372.226     2098640.686      387682.358
     2098278.414      387957.377
#Sta/Elev= 30
       0 3532.84    1.13 3532.54    31.4 3523.65      60 3508.97    88.7 3508.27
   115.2 3498.59   129.7  3490.2   227.3 3451.93   245.9 3441.31   263.5 3439.57
   273.3  3431.6     288 3424.73   402.1 3391.33     411 3387.07   437.5  3364.6
   445.6 3361.72     468 3359.94   478.3 3361.36   522.8 3362.86   560.2 3370.27
   627.4 3410.93   639.8 3413.65   735.8 3458.14   752.2    3461   768.6 3469.96
   822.3 3491.98   834.6 3493.14   860.7 3504.13   902.1 3515.78   918.4 3514.68
#Mann= 4 ,-1 , 0
       0     .06       0    1.13      .1       0   445.6    .045       0
   478.3      .1       0
#XS Ineff= 2 , 0
                          490.18         3366.07
Permanent Ineff=
       F       F
Bank Sta=445.6,478.3
XS Rating Curve= 0 ,0
Exp/Cntr=0.3,0.1

Type RM Length L Ch R = 1 ,7778    ,499.4,499.3,487.1
XS GIS Cut Line= 2
2098804.03951792387196.1036989692098100.02660648387800.777365234
#Sta/Elev= 30
       0 3518.18     3.8  3515.3    30.9 3514.89      47 3504.66    77.6  3495.8
    93.7 3485.97   191.4 3442.75   248.8 3424.86   284.9 3411.62   319.5 3394.63
     338 3392.64   388.7 3371.79   450.2  3361.4   460.3 3350.39   483.8  3348.6
   493.9  3350.2   515.7 3352.39   535.8 3350.25   550.9 3358.61   570.7 3359.76
   603.2 3380.49   656.8  3402.4     673 3404.06   740.5 3425.86   787.6 3447.35
   799.6 3456.56     815 3460.39   834.1 3470.74   912.7 3490.22     928 3491.22
#Mann= 3 ,-1 , 0
       0      .1       0   460.3    .045       0   493.9      .1       0
#XS Ineff= 2 , 0
                          515.02         3355.72
Permanent Ineff=
       F       F
Bank Sta=460.3,493.9
XS Rating Curve= 0 ,0
Exp/Cntr=0.3,0.1

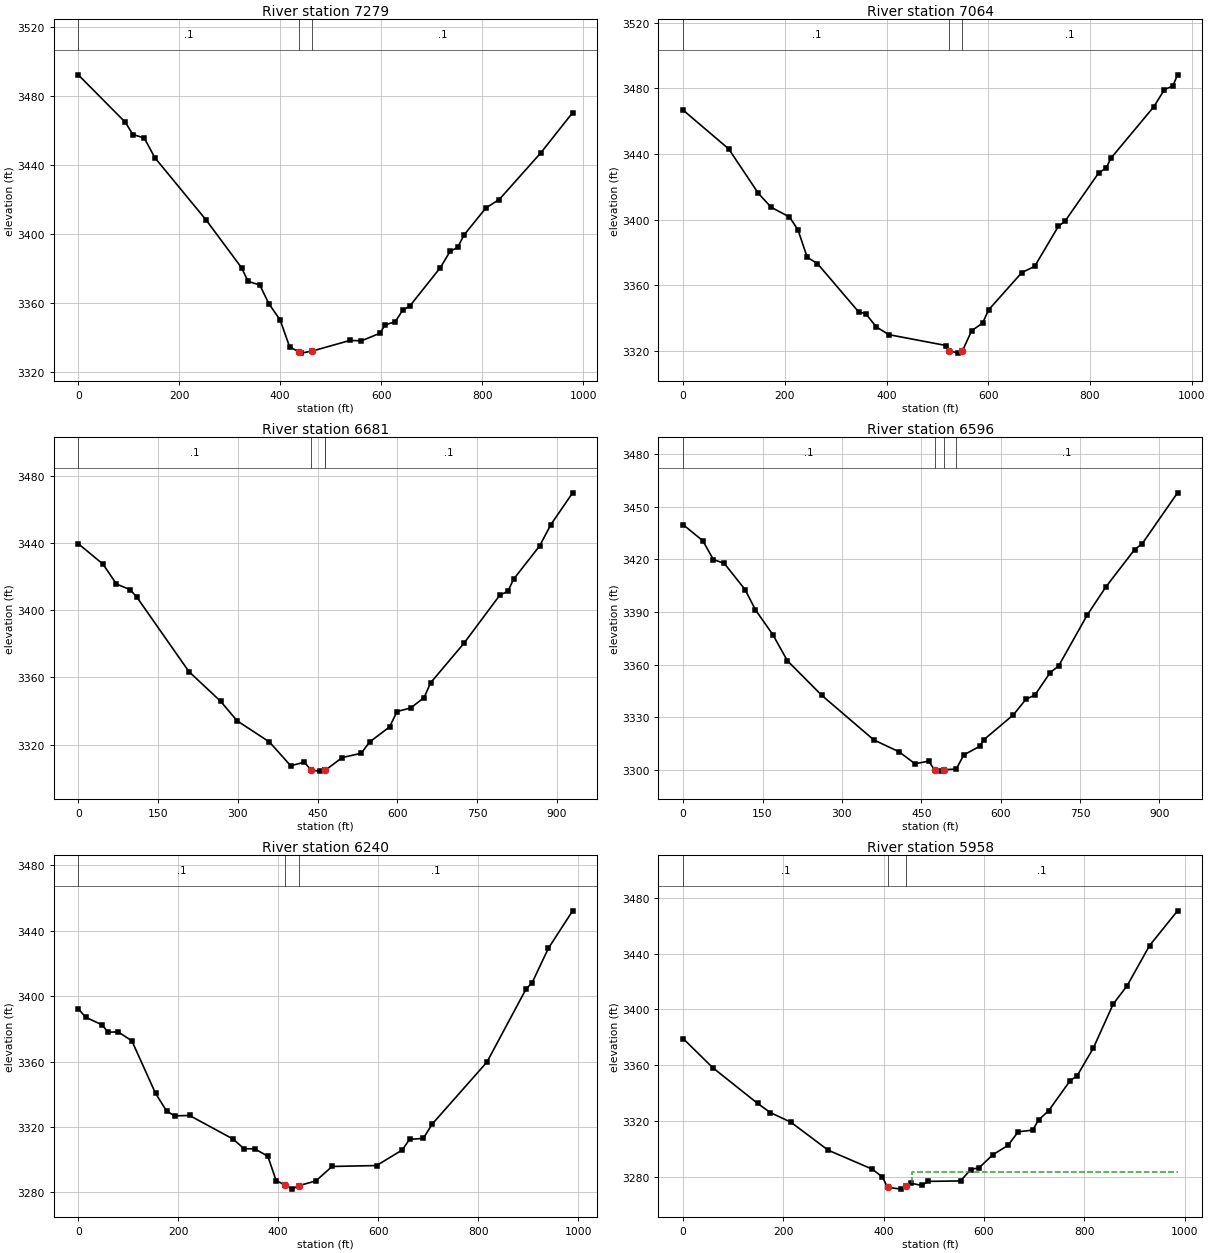
Type RM Length L Ch R = 1 ,7279    ,207.8,215.4,211
XS GIS Cut Line= 2
2098397.08846794386757.9922323042097927.06321296 387617.07200507
#Sta/Elev= 30
       0 3492.37    93.3 3464.79   108.2 3457.69   130.7 3455.72   151.7 3444.25
   253.3 3408.06   323.4 3380.39   336.4 3372.45   359.6 3370.32   377.5 3359.48
   399.9 3350.04   418.6 3334.44   436.3 3331.56   441.1 3330.77   463.6 3331.98
   538.3 3338.15   560.8 3337.91   598.2 3342.39   607.2 3347.06   628.1 3349.06
   642.4 3355.62     657 3358.22   717.4 3380.48   736.7 3389.95   751.5 3392.14
   764.4 3399.47   807.6 3415.11   833.8 3419.95     916 3446.98   979.3 3470.41
#Mann= 3 ,-1 , 0
       0      .1       0   436.3    .045       0   463.6      .1       0
Bank Sta=436.3,463.6
XS Rating Curve= 0 ,0
Exp/Cntr=0.3,0.1

Type RM Length L Ch R = 1 ,7064    ,377.3,382.9,383.2
XS GIS Cut Line= 2
2098311.66238968 386721.002961192097712.74752023387486.922938459
#Sta/Elev= 30
       0 3466.69    89.5 3443.12     148 3416.02     173 3407.58   209.1 3401.67
   225.8 3393.87   243.9 3377.17   264.1 3373.29   345.1 3343.91   359.1 3342.77
   379.9 3334.77   404.4 3330.04   517.3 3323.41   523.7 3320.33   539.9 3318.79
   549.3 3320.16   567.3  3332.4     589 3337.11   600.6 3345.06   666.1 3367.85
   691.3 3371.59   738.1 3396.05   750.6 3398.93   817.2 3428.48   832.1 3431.57
   841.4 3437.47   925.6 3468.75   946.6 3479.23     963 3481.41   972.3 3488.19
#Mann= 3 ,-1 , 0
       0      .1       0   523.7    .045       0   549.3      .1       0
Bank Sta=523.7,549.3
XS Rating Curve= 0 ,0
Exp/Cntr=0.3,0.1

Type RM Length L Ch R = 1 ,6681    ,83.3,85.2,86.2
XS GIS Cut Line= 2
2098144.68101859386546.804590953 2097427.7108143387138.520964369
#Sta/Elev= 30
       0 3439.52    46.4 3427.41    71.9 3415.54    97.4 3412.21   109.9 3407.86
     208 3363.53   267.6 3345.87   298.8 3334.22   359.4 3321.69   399.4 3307.55
     425 3309.62   438.5 3304.79   454.7 3304.34   463.6 3304.72   464.3 3304.82
   496.4 3312.41   531.9 3314.94     548 3321.68   585.5 3330.67   599.4 3339.78
   625.1 3341.89   650.4 3348.09   662.4 3356.79   725.3 3380.37   792.9 3409.03
   807.8 3411.18   818.5 3418.41   867.4 3438.15   888.6 3450.87   929.6 3469.76
#Mann= 4 ,-1 , 0
       0      .1       0   438.5    .045       0   463.6    .045       0
   464.3      .1       0
Bank Sta=438.5,463.6
XS Rating Curve= 0 ,0
Exp/Cntr=0.3,0.1

Type RM Length L Ch R = 1 ,6596    ,362,356.1,352
XS GIS Cut Line= 2
2098129.52857183386506.2870475422097362.54138908387039.427493369
#Sta/Elev= 30
       0 3439.81    37.1 3430.71    57.1 3419.97    77.7 3417.77     117 3402.84
   136.6 3391.28   169.6 3377.09   196.9  3362.3   261.5 3342.66   360.2 3317.14
   407.7  3310.4   438.3 3303.52   463.7 3305.04   475.2 3300.03   486.7 3299.34
   493.8 3300.15   515.93300.521   530.2 3308.56   560.5 3313.53   567.9 3317.18
   624.1 3331.49   647.6 3340.28   664.6  3342.7   693.6 3355.56   709.4 3359.29
   763.6  3388.4   798.9 3404.46   853.1 3425.69   867.3 3428.97   934.1    3458
#Mann= 4 ,-1 , 0
       0      .1       0   475.2    .045       0   493.8    .045       0
   515.9      .1       0
Bank Sta=475.2,493.8
XS Rating Curve= 0 ,0
Exp/Cntr=0.3,0.1

Type RM Length L Ch R = 1 ,6240    ,293,281.3,273.9
XS GIS Cut Line= 2
2097984.85067005386199.8318488382097204.53370073386807.384913513
#Sta/Elev= 30
       0 3392.35    14.6 3387.16    48.4 3382.38      59 3377.98    79.8 3378.18
   107.2  3372.7   154.6 3340.56   176.6 3329.84   192.6 3326.79   222.7 3327.04
   310.1 3312.52   331.5  3306.7   352.8 3306.61   379.1 3302.16   395.8 3287.21
   414.4 3284.32   427.6 3281.97     441 3284.09   475.2 3286.97   507.7 3295.84
   596.7 3296.39   648.2 3305.96   662.6 3312.45   690.2 3312.98   707.6 3321.65
   817.5 3359.72     896 3404.59   907.7 3408.17   940.4 3429.35   988.9 3452.25
#Mann= 3 ,-1 , 0
       0      .1       0   414.4    .045       0     441      .1       0
Bank Sta=414.4,441
XS Rating Curve= 0 ,0
Exp/Cntr=0.3,0.1

Type RM Length L Ch R = 1 ,5958    ,276.6,272.6,274
XS GIS Cut Line= 3
2097528.46602194385903.2538125272097364.34031253386553.997853364
2097136.86783808386771.392433379
#Sta/Elev= 30
       0 3379.15    59.1 3358.28   148.6 3332.69   174.1 3326.11   214.7 3319.31
   289.2 3299.24   377.2 3285.65   397.5 3279.94   407.6 3272.67   434.7 3271.36
   444.8 3273.32     455 3275.54   475.3 3274.03   488.8 3276.92   553.1 3277.22
   573.4  3285.4   590.3 3286.69   617.5 3295.99   647.8 3302.71   668.1 3312.42
     697 3313.59   708.6 3320.86   728.7 3327.45   771.4  3348.9   785.7 3352.61
   817.7 3372.19   857.4 3403.79   885.4 3417.07     930 3445.72   985.8 3470.61
#Mann= 3 ,-1 , 0
       0      .1       0   407.6    .045       0   444.8      .1       0
#XS Ineff= 2 , 0
                          456.88         3283.53
Permanent Ineff=
       F       F
Bank Sta=407.6,444.8
XS Rating Curve= 0 ,0
Exp/Cntr=0.3,0.1

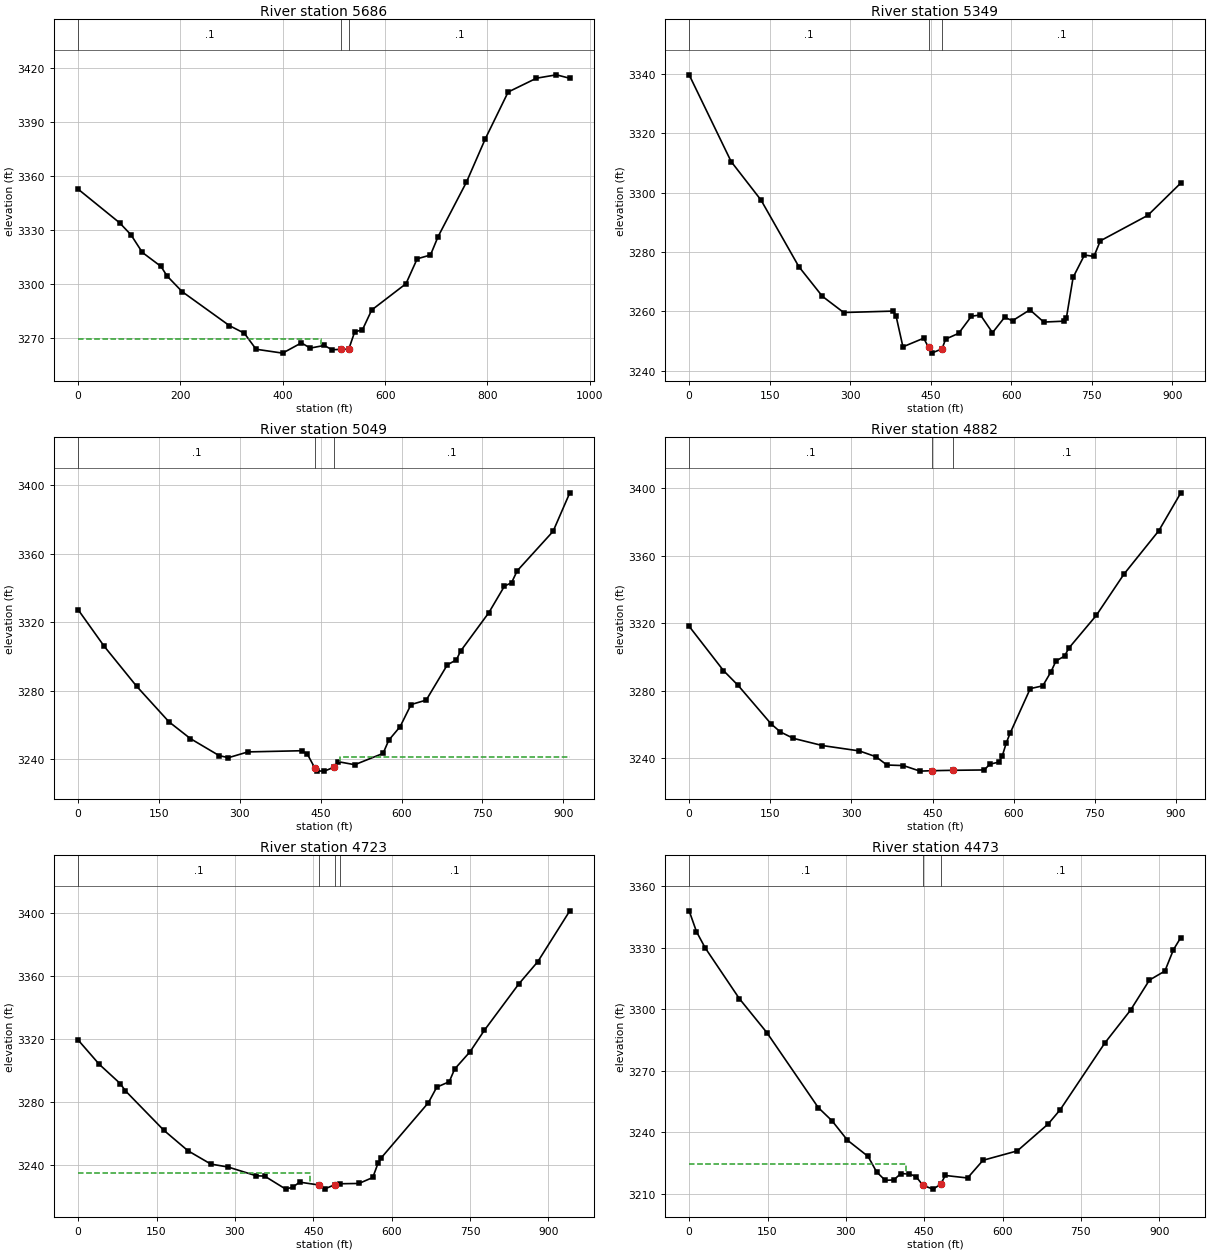
Type RM Length L Ch R = 1 ,5686    ,334.7,336.9,338.6
XS GIS Cut Line= 2
2097396.26145051385855.9381836542096949.95469684386706.960380619
#Sta/Elev= 30
       0 3352.55    81.1 3333.86   103.3  3327.2   125.5 3317.42     162 3309.63
   173.7 3304.38   203.3 3295.65   295.7 3276.77   324.8 3272.57   347.8 3263.67
   399.7 3261.51   436.4  3267.2   453.6  3264.3   481.2 3265.78     496  3263.4
   514.1 3263.59     529 3263.74   540.5 3273.28   555.7 3274.46   573.8 3285.45
   640.8 3300.05   662.7 3313.88   688.7 3315.99   703.5 3326.18     759 3356.46
   796.1 3380.65   840.5 3406.49   895.9 3414.16   934.8 3416.03     961 3414.11
#Mann= 3 ,-1 , 0
       0      .1       0   514.1    .045       0     529      .1       0
#XS Ineff= 2 , 0
          474.42 3269.31
Permanent Ineff=
       F       F
Bank Sta=514.1,529
XS Rating Curve= 0 ,0
Exp/Cntr=0.3,0.1

Type RM Length L Ch R = 1 ,5349    ,294.3,300,302.1
XS GIS Cut Line= 3
     2097304.795      385760.594     2096963.734      386060.666
     2096604.276      386350.147
#Sta/Elev= 30
       0 3339.76    78.2 3310.51   133.9 3297.51   204.2  3275.1   248.1 3265.08
   287.8 3259.61   379.8 3260.08   385.5 3258.33   398.2 3248.03   436.8 3250.94
     446 3247.84   451.7 3245.91   470.9 3247.35   477.8 3250.64     502 3252.59
   525.7 3258.34   542.5 3258.79     565 3252.81   587.6 3257.99   602.3 3256.84
   634.7 3260.52   660.5 3256.38   698.4 3256.69   702.7 3257.83   715.2 3271.48
   736.3 3278.99     754 3278.53   765.8 3283.77   854.3 3292.37   915.8 3303.28
#Mann= 3 ,-1 , 0
       0      .1       0     446    .045       0   470.9      .1       0
Bank Sta=446,470.9
XS Rating Curve= 0 ,0
Exp/Cntr=0.3,0.1

Type RM Length L Ch R = 1 ,5049    ,164.8,167.1,168.6
XS GIS Cut Line= 3
      2097244.78      385633.876     2096824.602      385809.102
     2096396.807      385969.357
#Sta/Elev= 30
       0 3327.33    48.1 3306.09   108.3 3282.72   168.5 3261.89   208.3 3252.08
   261.7 3242.14   278.9 3240.95     315 3244.32   414.9 3245.01   425.2 3243.08
   438.8 3235.04     443 3233.21   456.8  3233.1   475.5 3235.51   482.5  3238.6
   513.2 3236.85   565.7 3243.46   576.3 3251.18   597.3 3259.04   617.6 3271.96
   645.7 3274.56   684.9 3295.15   701.7 3298.07   709.4 3303.12   761.9  3325.6
   790.9 3341.11     804 3343.07   814.5 3350.03   881.1 3373.09   912.1 3395.56
#Mann= 3 ,-1 , 0
       0      .1       0   438.8    .045       0   475.5      .1       0
#XS Ineff= 2 , 0
                          485.39          3241.6
Permanent Ineff=
       F       F
Bank Sta=438.8,475.5
XS Rating Curve= 0 ,0
Exp/Cntr=0.3,0.1

Type RM Length L Ch R = 1 ,4882    ,124.4,132.9,124.6
XS GIS Cut Line= 2
2097212.20222201385536.3980038472096333.98570672385771.068974326
#Sta/Elev= 30
       0 3318.09    63.4  3291.9    90.6 3283.08   151.7 3260.24   168.7 3255.56
   192.5 3251.77   246.5 3247.48   314.7 3244.31   345.3 3240.88   365.7 3235.97
   396.2 3235.63   426.8 3232.35   448.6  3232.6   487.6 3232.84   545.7 3233.04
   555.8 3236.47   572.8 3237.69   578.8  3241.2   586.4 3249.17   593.2 3254.66
   630.6 3281.19   653.8 3282.86   669.2 3291.33   678.1 3297.56     694 3300.45
     702  3305.2   752.6 3324.51   803.9    3349   868.3 3374.69     909 3397.12
#Mann= 3 ,-1 , 0
       0      .1       0   448.6    .045       0   487.6      .1       0
Bank Sta=448.6,487.6
XS Rating Curve= 0 ,0
Exp/Cntr=0.3,0.1

Type RM Length L Ch R = 1 ,4723    ,239.7,249.2,244.7
XS GIS Cut Line= 3
2097180.89730641385430.9714108962096696.14930641385519.568410896
2096254.01530641385592.565410896
#Sta/Elev= 30
       0 3319.26    40.5 3303.79    80.5 3291.58    90.5 3286.95   163.9 3261.91
   210.2 3248.85   253.9 3240.39   287.3 3238.48   340.7 3232.95   356.9 3232.73
   397.3 3224.45   410.7 3225.73     424 3228.88   461.2 3227.07   472.5 3224.66
   490.7 3227.19   500.6 3227.86   537.3 3228.05   563.9 3231.85   573.9 3240.94
   580.5 3244.52   670.3 3279.41   686.3 3289.28   710.2 3292.74   720.5 3300.78
   750.1 3311.84   777.6 3325.53   843.2 3354.87   879.8 3369.14   940.9  3401.4
#Mann= 4 ,-1 , 0
       0      .1       0   461.2    .045       0   490.7    .045       0
   500.6      .1       0
#XS Ineff= 2 , 0
          442.95 3234.75
Permanent Ineff=
       F       F
Bank Sta=461.2,490.7
XS Rating Curve= 0 ,0
Exp/Cntr=0.3,0.1

Type RM Length L Ch R = 1 ,4473    ,316.3,312.7,306.3
XS GIS Cut Line= 2
2097194.45580629385307.2183414952096254.33222517385261.147966922
#Sta/Elev= 30
       0 3347.93      14  3337.8    30.5 3329.97    96.1 3305.17   148.7 3288.65
   247.2 3252.11   273.5 3245.69   303.1 3236.23   342.5 3228.34   358.9 3220.78
   375.4 3216.69   391.8 3216.88   404.9 3219.93   421.3 3219.84   434.5  3218.5
   447.6 3214.23     467 3212.41   481.5 3214.77   490.3 3219.06     533 3217.84
   562.6 3226.46   628.3 3231.04   687.4 3244.15   710.4 3251.09   795.8 3283.57
   845.1  3299.6   881.2 3314.22   910.8 3318.61   927.2 3329.03   941.3 3334.94
#Mann= 3 ,-1 , 0
       0      .1       0   447.6    .045       0   481.5      .1       0
#XS Ineff= 2 , 0
          414.65 3224.78
Permanent Ineff=
       F       F
Bank Sta=447.6,481.5
XS Rating Curve= 0 ,0
Exp/Cntr=0.3,0.1

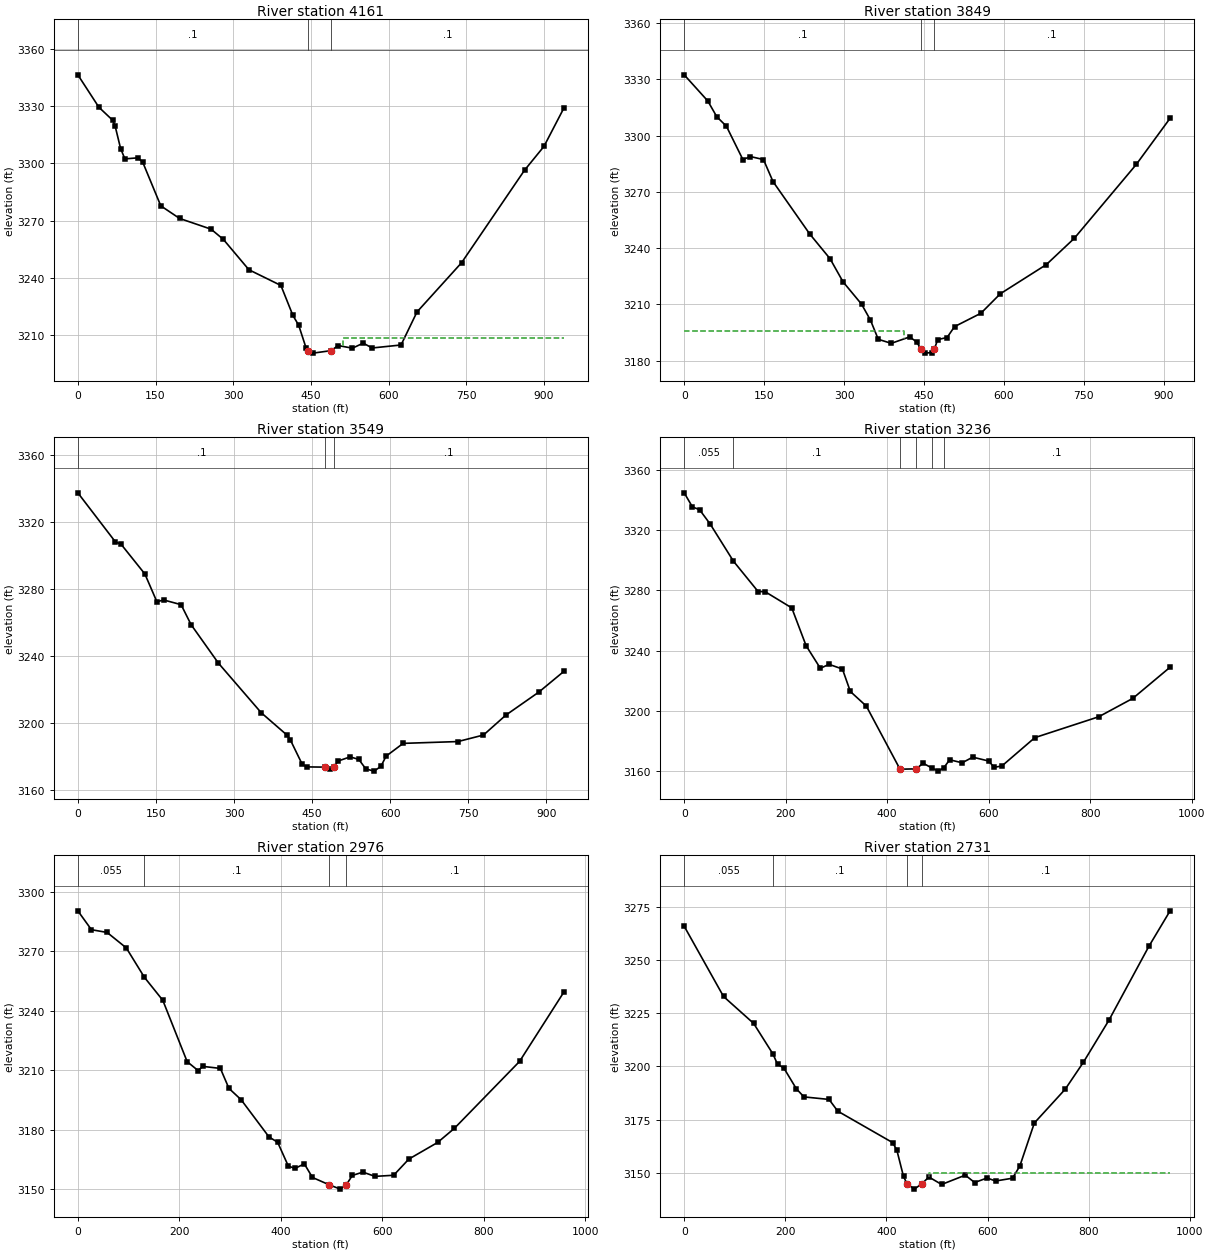
Type RM Length L Ch R = 1 ,4161    ,312.2,312.1,308.7
XS GIS Cut Line= 3
2097056.24468257384763.0120418562096847.48829779384954.492036173
2096225.53824106385160.369022544
#Sta/Elev= 30
       0  3346.5    40.7 3329.48    67.4 3322.64    71.9 3319.77    82.6 3307.82
    90.9 3302.39   116.4 3302.97   125.3 3300.68   160.2 3277.77   196.5 3271.16
   257.3 3265.53   281.1 3260.15   330.4 3244.24   392.2    3236   415.3  3220.3
   426.5 3215.14   440.6 3203.37   444.7 3201.75   454.4  3200.5   488.8  3201.8
   502.8 3204.47   530.4  3203.1   551.1 3205.75   568.4  3203.2   624.2 3204.77
     655  3222.1   741.2 3247.96   862.7 3296.46   900.2 3308.95   938.4 3328.92
#Mann= 3 ,-1 , 0
       0      .1       0   444.7    .045       0   488.8      .1       0
#XS Ineff= 2 , 0
                          511.82         3208.24
Permanent Ineff=
       F       F
Bank Sta=444.7,488.8
XS Rating Curve= 0 ,0
Exp/Cntr=0.3,0.1

Type RM Length L Ch R = 1 ,3849    ,296.3,300,303.4
XS GIS Cut Line= 3
     2096972.807      384588.994     2096543.779      384739.666
     2096117.258      384903.497
#Sta/Elev= 30
       0 3332.39    44.2 3318.48    61.2 3310.02    79.2 3304.99   110.1 3287.21
   124.2 3288.81   148.7 3287.23   166.7 3275.44   235.5 3247.54   273.7 3234.33
     298 3222.03   332.8  3210.1   349.4 3201.64   364.1 3191.39   388.5 3189.24
   423.2 3192.68   436.2 3189.92   444.1 3186.24     451 3184.02   465.1 3184.32
   469.2 3186.08   475.6 3191.24   493.2 3192.35   507.2 3198.15   556.6 3205.27
   593.1 3215.67   679.5 3231.24   731.7 3245.18   848.1  3284.6   911.6 3309.23
#Mann= 3 ,-1 , 0
       0      .1       0   444.1    .045       0   469.2      .1       0
#XS Ineff= 2 , 0
          413.02 3195.96
Permanent Ineff=
       F       F
Bank Sta=444.1,469.2
XS Rating Curve= 0 ,0
Exp/Cntr=0.3,0.1

Type RM Length L Ch R = 1 ,3549    ,295.5,313.1,286.4
XS GIS Cut Line= 3
     2096951.458      384478.829     2096469.486      384453.136
      2096019.22      384437.983
#Sta/Elev= 30
       0 3337.58    72.3 3308.25    82.8    3307   128.8 3289.15   151.8  3272.6
   164.9 3273.66   198.3 3270.86   217.5 3258.94     270 3235.97   352.2 3206.39
   401.5  3193.1   408.1 3190.21   431.1 3175.51   440.2 3174.07   475.2 3173.93
   483.6 3173.01   491.8 3174.23   500.1  3177.6     523 3180.06   539.6 3178.53
   553.2 3172.83     569 3171.55   582.1 3174.41     592 3180.47   624.8 3188.11
     730 3189.19   779.1 3193.09   821.9 3204.92   885.5 3218.73   933.2 3230.99
#Mann= 3 ,-1 , 0
       0      .1       0   475.2    .045       0   491.8      .1       0
Bank Sta=475.2,491.8
XS Rating Curve= 0 ,0
Exp/Cntr=0.3,0.1

Type RM Length L Ch R = 1 ,3236    ,228,259.9,233.6
XS GIS Cut Line= 2
 2096903.6365668384007.1699590252096005.26426264384338.300776265
#Sta/Elev= 30
       0 3344.62    16.2 3335.29    30.2 3333.46    51.2 3323.94   97.033299.327
   145.6 3279.22   159.5  3279.1     212 3268.36   240.2 3243.34   268.3 3228.35
   285.4 3230.97   311.8 3227.86   327.4 3212.98   358.9  3203.3   425.3 3161.48
   457.4 3161.72   470.7 3165.47     488 3162.29   500.8 3160.21   511.5 3162.45
   523.2 3167.73   547.7 3165.73   568.6 3169.47   600.1 3166.89   610.6 3162.72
     626 3163.61     691 3182.41   816.9 3196.23   884.1 3208.43   957.5 3229.07
#Mann= 6 ,-1 , 0
       0    .055       0   97.03      .1       0   425.3    .045       0
   457.4    .045       0     488    .045       0   511.5      .1       0
Bank Sta=425.3,457.4
XS Rating Curve= 0 ,0
Exp/Cntr=0.3,0.1

Type RM Length L Ch R = 1 ,2976    ,244.3,245.1,242.7
XS GIS Cut Line= 2
2096805.85154042383834.2315345222095889.77093603 384114.10906005
#Sta/Elev= 30
       0 3290.44    26.8 3280.92    57.7 3279.54    95.5 3271.75  131.31 3256.88
   167.5 3245.32   215.5 3214.38     237 3209.89   246.4 3211.99     281 3210.97
   297.9 3200.89   321.9 3195.18   376.8 3176.43   393.9 3173.72     415  3161.7
   428.2 3160.54   446.5 3162.85   462.5 3155.98   495.3  3152.3   517.4 3150.09
   528.9 3152.13   541.1 3156.99     562 3158.67   585.8 3156.52   622.6 3157.08
   652.5 3165.23   709.3 3173.63   742.3 3180.74   870.8 3214.49   957.9 3249.36
#Mann= 4 ,-1 , 0
       0    .055       0  131.31      .1       0   495.3    .045       0
   528.9      .1       0
Bank Sta=495.3,528.9
XS Rating Curve= 0 ,0
Exp/Cntr=0.3,0.1

Type RM Length L Ch R = 1 ,2731    ,247.6,244.7,246.6
XS GIS Cut Line= 2
2096690.53163407383569.9027604122095813.32290823383962.508733722
#Sta/Elev= 30
       0 3265.93    77.8 3232.91   137.4 3220.24  175.533205.879   184.6 3201.04
     197 3199.32   221.7 3189.57   236.8  3185.7   286.5 3184.51   303.8 3178.99
   412.2 3164.22   420.5 3160.78   433.8 3148.29   440.9  3144.8   455.3 3142.34
   470.2 3144.91   484.1 3148.03   509.2 3144.53     556 3148.91   574.5 3145.44
   599.1 3147.58   615.8 3146.16   649.4 3147.47   663.9 3153.21   692.6 3173.44
   753.7 3189.33   789.6 3201.98   840.2 3221.79     919 3256.43   961.1 3273.18
#Mann= 4 ,-1 , 0
       0    .055       0  175.53      .1       0   440.9    .045       0
   470.2      .1       0
#XS Ineff= 2 , 0
                           484.8         3150.03
Permanent Ineff=
       F       F
Bank Sta=440.9,470.2
XS Rating Curve= 0 ,0
Exp/Cntr=0.3,0.1

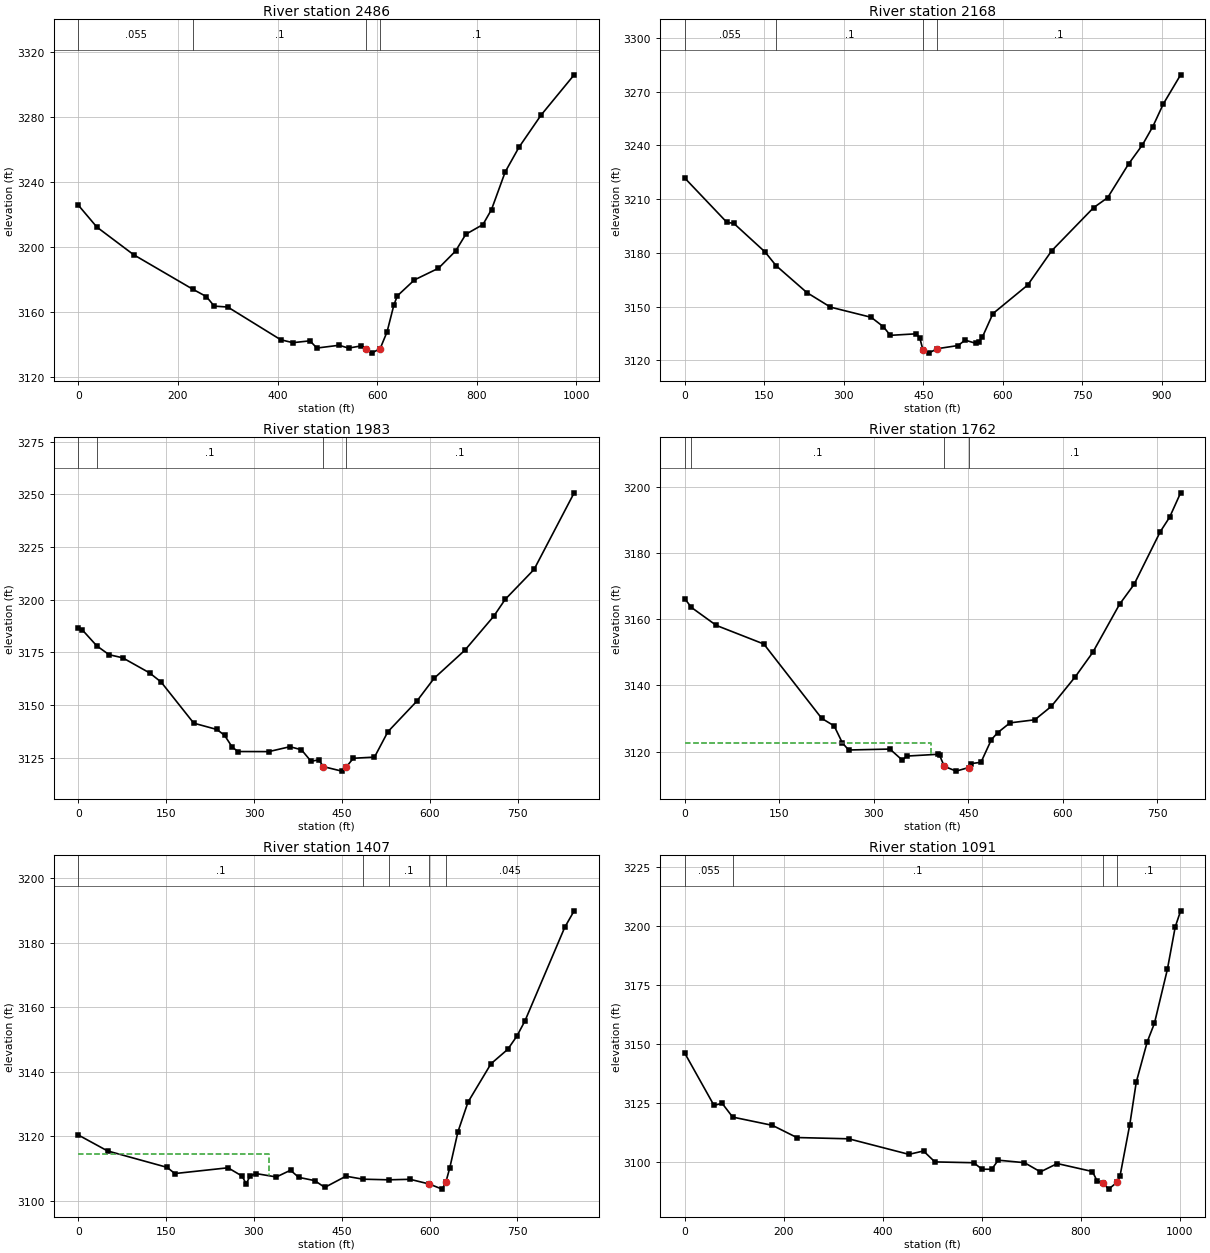
Type RM Length L Ch R = 1 ,2486    ,315.3,318.1,321.9
XS GIS Cut Line= 2
2096646.47683839383444.2170197812095696.70727259383742.234755297
#Sta/Elev= 30
       0 3225.89    37.2 3212.42   110.9 3195.45  229.423174.266   257.1 3169.66
   272.8 3163.81     300 3163.25   406.3 3143.13   430.7 3141.33   465.1 3142.46
   478.8 3138.02   523.5 3139.74   542.4 3137.99   568.2 3139.36   578.5 3137.44
   588.8  3134.9     606 3137.71   619.8 3147.98   633.5 3164.53   640.4 3170.11
   674.8 3179.94     723  3187.1   757.3 3197.66   777.9 3207.99   812.3 3213.98
   829.5 3223.21     857 3246.37   884.6 3261.51   929.3 3281.43   995.4 3306.06
#Mann= 4 ,-1 , 0
       0    .055       0  229.42      .1       0   578.5    .045       0
     606      .1       0
Bank Sta=578.5,606
XS Rating Curve= 0 ,0
Exp/Cntr=0.3,0.1

Type RM Length L Ch R = 1 ,2168    ,180.6,184.4,184
XS GIS Cut Line= 2
2096659.43413124383327.6013841442095723.91758757383337.967218423
#Sta/Elev= 30
       0 3221.72    79.4 3197.01    92.5 3196.44   151.6 3180.43  172.113172.876
   230.3 3157.82   274.9 3149.68   351.7    3144   374.7 3138.74   387.8 3133.93
     437 3134.79   443.6 3132.23   449.6 3125.62   459.9    3124   476.7 3126.49
   515.8 3128.25   528.9 3131.26   548.6 3129.52   555.1 3130.48   561.7 3133.06
   581.4 3146.06     647    3162   692.3 3181.14   771.4 3205.22   797.9 3210.79
   837.3 3229.57   863.6 3240.29   883.2 3250.51   902.9  3263.1   935.6 3279.37
#Mann= 4 ,-1 , 0
       0    .055       0  172.11      .1       0   449.6    .045       0
   476.7      .1       0
Bank Sta=449.6,476.7
XS Rating Curve= 0 ,0
Exp/Cntr=0.3,0.1

Type RM Length L Ch R = 1 ,1983    ,220.4,221.3,218.8
XS GIS Cut Line= 2
2096599.83058413383166.9309528222095753.71936112 383147.49501355
#Sta/Elev= 30
       0 3186.45     6.7 3185.66   31.523178.035    52.6 3173.83    75.6 3172.39
   121.5 3165.22   141.2 3160.89     197 3141.32   236.4 3138.32   249.5 3135.58
   262.6 3129.96   272.5 3127.84     325  3127.8   361.2 3130.13   380.8 3128.68
   397.2 3123.21   410.3 3123.88   418.3 3120.67   449.7 3118.53   457.2 3120.47
   469.4 3124.64   505.5 3125.19   528.4 3137.26   577.7 3151.75   607.2 3162.62
   659.7 3175.96   708.9 3192.07   728.6 3200.14   777.9 3214.37   846.3 3250.76
#Mann= 4 ,-1 , 0
       0    .055       0   31.52      .1       0   418.3    .045       0
   457.2      .1       0
Bank Sta=418.3,457.2
XS Rating Curve= 0 ,0
Exp/Cntr=0.3,0.1

Type RM Length L Ch R = 1 ,1762    ,280.7,280.7,280.7
XS GIS Cut Line= 2
2096603.71777199382954.4313501062095817.21009608382932.403952264
#Sta/Elev= 30
       0 3166.14   10.46 3163.52    49.9  3158.1   125.4 3152.47   217.3 3130.01
     237 3127.75   250.1 3122.59     260 3120.47   325.5 3120.75   345.3 3117.38
   351.9 3118.63   401.1 3119.17   404.4 3118.85   411.7 3115.55   430.5 3114.09
   450.4 3115.17   453.6 3116.34     470 3116.76   486.5  3123.6   496.3 3125.67
     516 3128.66   555.4 3129.59   581.6 3133.64   619.6 3142.57   647.3 3149.92
   689.9 3164.47   712.9 3170.46   754.6 3186.42   769.3 3190.74   786.8 3198.12
#Mann= 4 ,-1 , 0
       0    .055       0   10.46      .1       0   411.7    .045       0
   450.4      .1       0
#XS Ineff= 2 , 0
          390.23 3122.53
Permanent Ineff=
       F       F
Bank Sta=411.7,450.4
XS Rating Curve= 0 ,0
Exp/Cntr=0.3,0.1

Type RM Length L Ch R = 1 ,1407    ,316.4,316.4,317.8
XS GIS Cut Line= 3
2096587.21623879382531.1977936582096377.30809464382520.831959379
2095770.90678933382715.191352107
#Sta/Elev= 30
       0 3120.34    49.9  3115.4   151.7  3110.3   164.8 3108.38   255.7 3110.17
   279.7  3107.6   286.7 3105.22   293.6 3107.66   303.9 3108.36   338.3 3107.33
   362.5 3109.41   376.3 3107.21   403.8 3106.19     421 3104.09   457.1 3107.56
   486.33106.633   530.63106.441   566.6  3106.6   599.4 3105.14   621.4 3103.55
  627.63 3105.61   634.5 3110.13   648.4 3121.29   665.6 3130.52   704.9 3142.44
   733.6 3146.93   749.3 3151.06     763 3155.76     831  3184.8     847 3189.89
#Mann= 5 ,-1 , 0
       0      .1       0   486.3    .045       0   530.6      .1       0
   599.4    .045       0  627.63    .045       0
#XS Ineff= 2 , 0
          326.39 3114.39
Permanent Ineff=
       F       F
Bank Sta=599.4,627.63
XS Rating Curve= 0 ,0
Exp/Cntr=0.3,0.1

Type RM Length L Ch R = 1 ,1091    ,312.6,312.6,312.6
XS GIS Cut Line= 2
2096717.74194905382415.4079676072095716.14321186382407.633591898
#Sta/Elev= 30
       0 3146.07      59 3123.93    75.4 3124.82   96.67 3118.98     177 3115.47
   226.3  3110.3   331.3 3109.76   452.7 3103.16   482.2 3104.59   505.2 3099.96
   583.7 3099.61   600.3 3096.85     620 3096.84   633.1 3100.69   686.2 3099.63
   718.4 3095.74   752.4 3099.26   823.4 3095.88   833.3 3091.73   844.5 3091.02
   856.2 3088.41   872.6 3091.23   879.2    3094   898.9  3115.8     912 3133.83
   934.2 3150.93   948.7 3158.78   974.8 3181.61   990.7 3199.66  1001.6 3206.49
#Mann= 4 ,-1 , 0
       0    .055       0   96.67      .1       0   844.5    .045       0
   872.6      .1       0
Bank Sta=844.5,872.6
XS Rating Curve= 0 ,0
Exp/Cntr=0.3,0.1