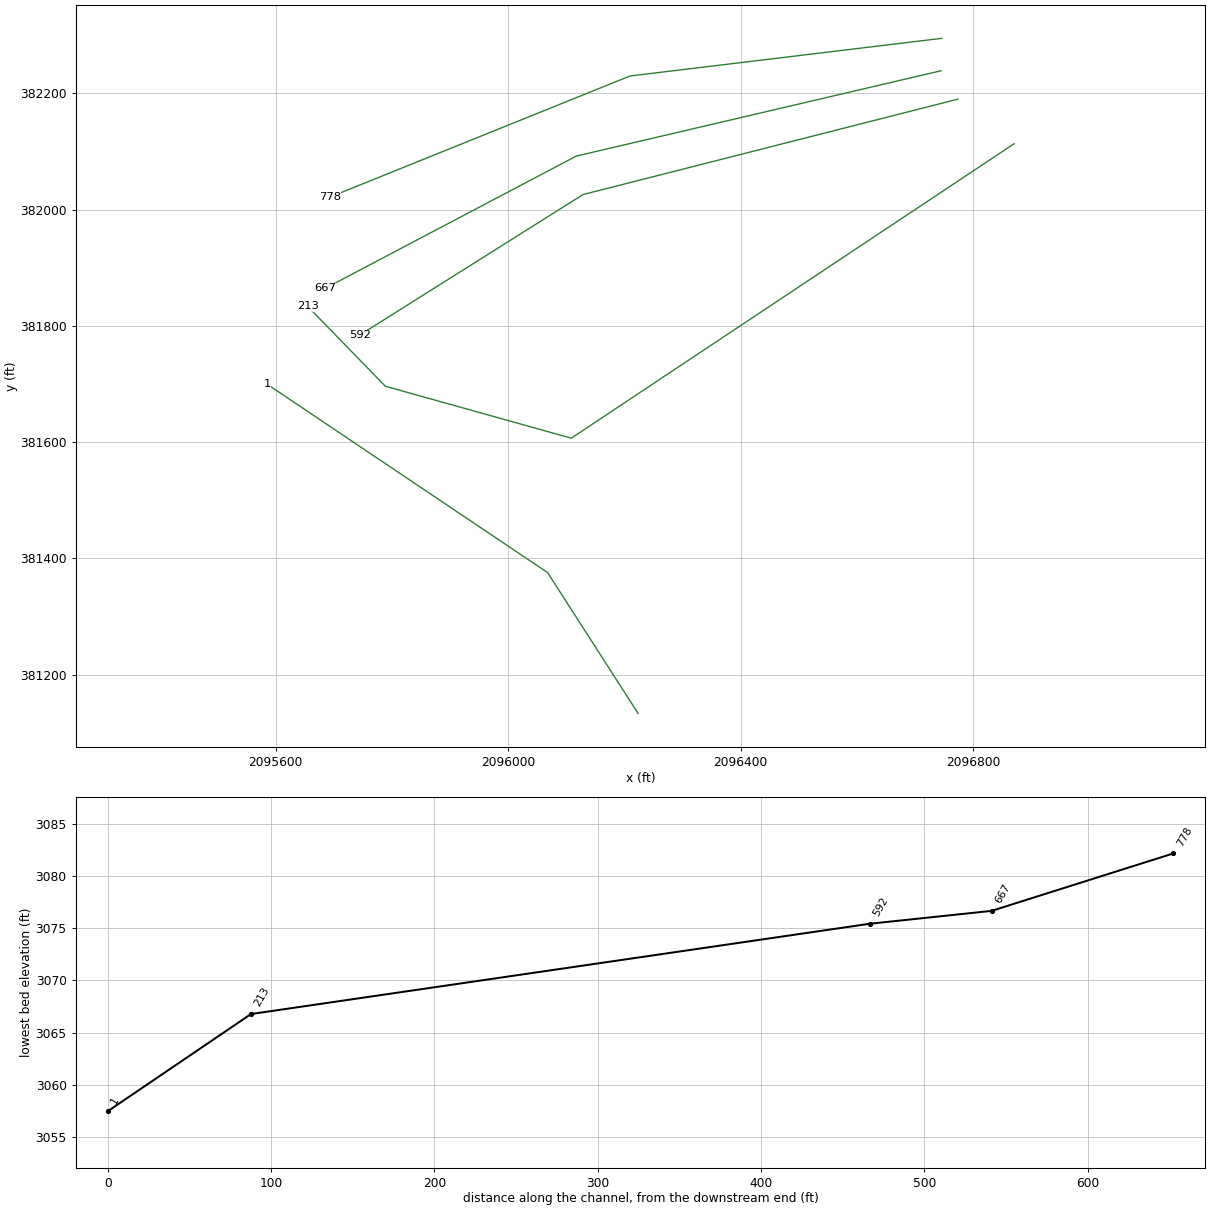
HEC-RAS study JOBKNOBBR1.prj: JOBKNOBBR1

--- JOBKNOBBR1.g01 (geometry) --- (continued)

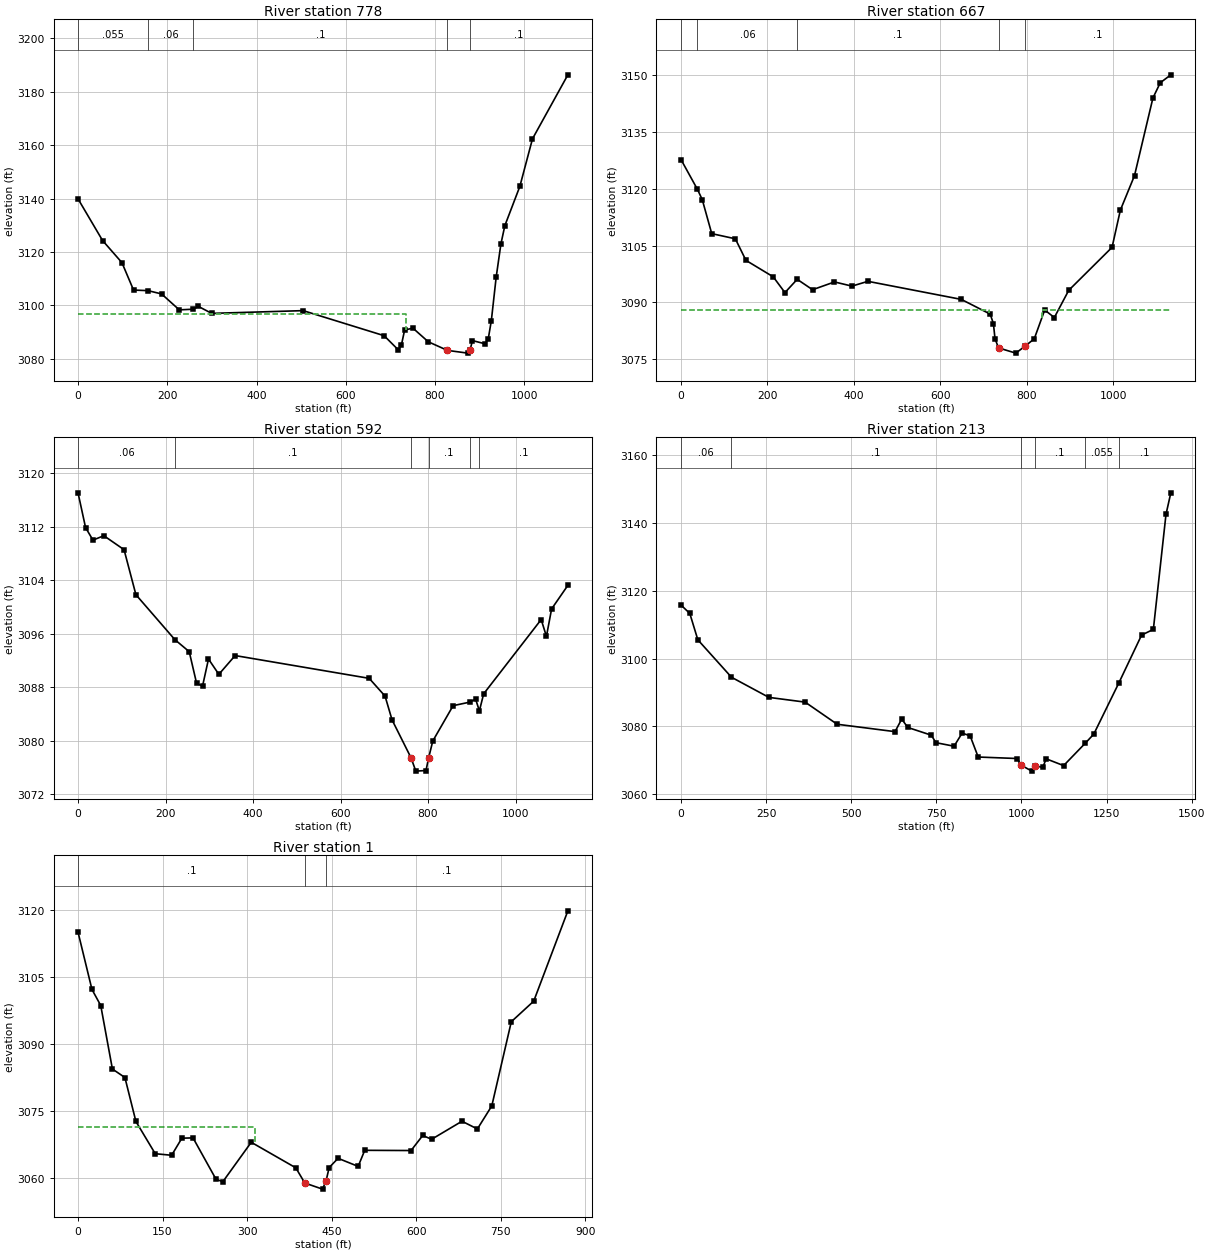
Type RM Length L Ch R = 1 ,778     ,111.4,111.4,111.4
XS GIS Cut Line= 3
2096746.24799332382294.9051441162096209.81606939382230.118679873
2095692.82008473382021.506265012
#Sta/Elev= 30
       0 3139.86      55 3124.28    98.4    3116   124.4 3105.75  156.74 3105.53
   187.2  3104.3   226.9 3098.34  257.74 3098.58   269.9 3099.61   299.6 3097.02
   504.5 3098.05   685.9 3088.68   717.8 3083.36   724.8 3085.26   731.9 3090.76
   750.4 3091.52     785 3086.39     828 3083.17   873.4 3082.15   878.4 3083.21
     884 3086.84   912.3 3085.64   919.4 3087.52   926.3 3094.34   937.1 3110.54
   947.7 3122.98   956.5 3129.82   990.2 3144.55  1018.5 3162.34  1097.8 3186.28
#Mann= 5 ,-1 , 0
       0    .055       0  156.74     .06       0  257.74      .1       0
     828    .045       0   878.4      .1       0
#XS Ineff= 2 , 0
          734.34 3096.89
Permanent Ineff=
       F       F
Bank Sta=828,878.4
XS Rating Curve= 0 ,0
Exp/Cntr=0.5,0.3

Type RM Length L Ch R = 1 ,667     ,74.5,74.5,74.5
XS GIS Cut Line= 3
2096745.10479216382239.1567216682096117.39593861382092.307402718
2095685.48617699381864.834928266
#Sta/Elev= 30
       0 3127.67   38.17 3119.78    49.2  3117.1    71.1 3108.14   125.7 3106.78
   150.2  3101.1   213.3 3096.76   240.4  3092.6  268.74  3096.1   304.3 3093.36
     355 3095.41   395.3 3094.31   432.3 3095.57   648.3 3090.81     715 3086.94
   722.5 3084.45   726.2 3080.45   734.4 3078.02   774.4 3076.65   796.6 3078.57
     817 3080.42   841.1 3088.02   863.4 3086.03   896.7  3093.2   996.9 3104.53
  1016.1 3114.33  1048.8 3123.43  1091.4 3143.89  1108.4  3147.9  1132.8 3149.99
#Mann= 5 ,-1 , 0
       0    .055       0   38.17     .06       0  268.74      .1       0
   734.4    .045       0   796.6      .1       0
#XS Ineff= 2 , 0
             712    3088     834            3088
Permanent Ineff=
       F       F
Bank Sta=734.4,796.6
XS Rating Curve= 0 ,0
Exp/Cntr=0.5,0.3

Type RM Length L Ch R = 1 ,592     ,378.9,378.9,378.9
XS GIS Cut Line= 3
2096773.89877627382190.2069486852096128.91353225 382026.08123927
2095744.51384441381784.211772764
#Sta/Elev= 30
       0 3117.08    17.2 3111.88    34.1    3110      59 3110.66   105.2 3108.57
   132.3 3101.83  221.24 3095.11   254.2  3093.3   271.1 3088.54   284.7 3088.17
   298.2  3092.2   321.9 3089.91   359.1 3092.72   665.5 3089.31   701.8 3086.65
   717.8 3083.09   761.3  3077.4   772.1 3075.42   795.4 3075.51   801.2 3077.34
   810.9 3079.93   857.4 3085.22   895.6 3085.75   908.8  3086.2  917.43 3084.44
   927.2 3086.99  1058.7 3098.11  1070.7 3095.59  1082.5  3099.7  1119.7 3103.23
#Mann= 6 ,-1 , 0
       0     .06       0  221.24      .1       0   761.3    .045       0
   801.2      .1       0   895.6    .055       0  917.43      .1       0
Bank Sta=761.3,801.2
XS Rating Curve= 0 ,0
Exp/Cntr=0.5,0.3

Type RM Length L Ch R = 1 ,213     ,87.7,87.7,87.7
XS GIS Cut Line= 4
2096870.63800467382113.5030442362096108.74918517381606.872893859
2095788.70405181381696.2782145142095655.24393547381833.625518708
#Sta/Elev= 30
       0 3115.79    25.9 3113.31    49.5 3105.53  148.36 3094.48   258.3 3088.54
   364.7 3087.14   458.7 3080.61   628.7 3078.43   648.4 3082.14   666.1 3079.67
   735.1 3077.39     749 3075.17   802.1 3074.13   825.8    3078   849.3 3077.19
     873 3070.94   987.7  3070.5   998.5 3068.58  1030.4 3066.78  1039.5 3068.32
  1062.6 3067.89  1072.8 3070.41  1123.9 3068.41 1186.89 3074.95  1212.5  3077.7
 1285.89 3092.75  1352.9 3106.92  1387.5 3108.61  1424.6 3142.54  1438.8  3148.9
#Mann= 6 ,-1 , 0
       0     .06       0  148.36      .1       0   998.5    .045       0
  1039.5      .1       0 1186.89    .055       0 1285.89      .1       0
Bank Sta=998.5,1039.5
XS Rating Curve= 0 ,0
Exp/Cntr=0.3,0.1

Type RM Length L Ch R = 1 ,1       ,1,1,1
XS GIS Cut Line= 3
2096223.65583131 381133.342755662096068.00160859381375.573883325
2095585.38141506381699.776761417
#Sta/Elev= 30
       0 3115.01    24.7 3102.19    40.3 3098.59      61 3084.37    83.2 3082.47
   102.7 3072.63     137 3065.41   166.1 3065.06   184.3 3068.89   204.1 3068.95
     245 3059.66   257.1 3059.16   307.4 3067.97   386.5 3062.25   402.4 3058.85
   433.9 3057.48   440.3  3059.4   445.7 3062.32   461.5 3064.38   497.1 3062.57
   508.8 3066.17     591 3066.12   611.7 3069.49   627.5 3068.64   681.4 3072.68
   708.7 3070.95   734.3 3076.12   768.9 3094.96   808.7 3099.57   869.3 3119.79
#Mann= 3 ,-1 , 0
       0      .1       0   402.4    .045       0   440.3      .1       0
#XS Ineff= 2 , 0
          313.92 3071.44
Permanent Ineff=
       F       F
Bank Sta=402.4,440.3
XS Rating Curve= 0 ,0
Exp/Cntr=0.3,0.1
LCMann Table=0

Chan Stop Cuts=-1
Use User Specified Reach Order=0
Composite Channel Slope=5